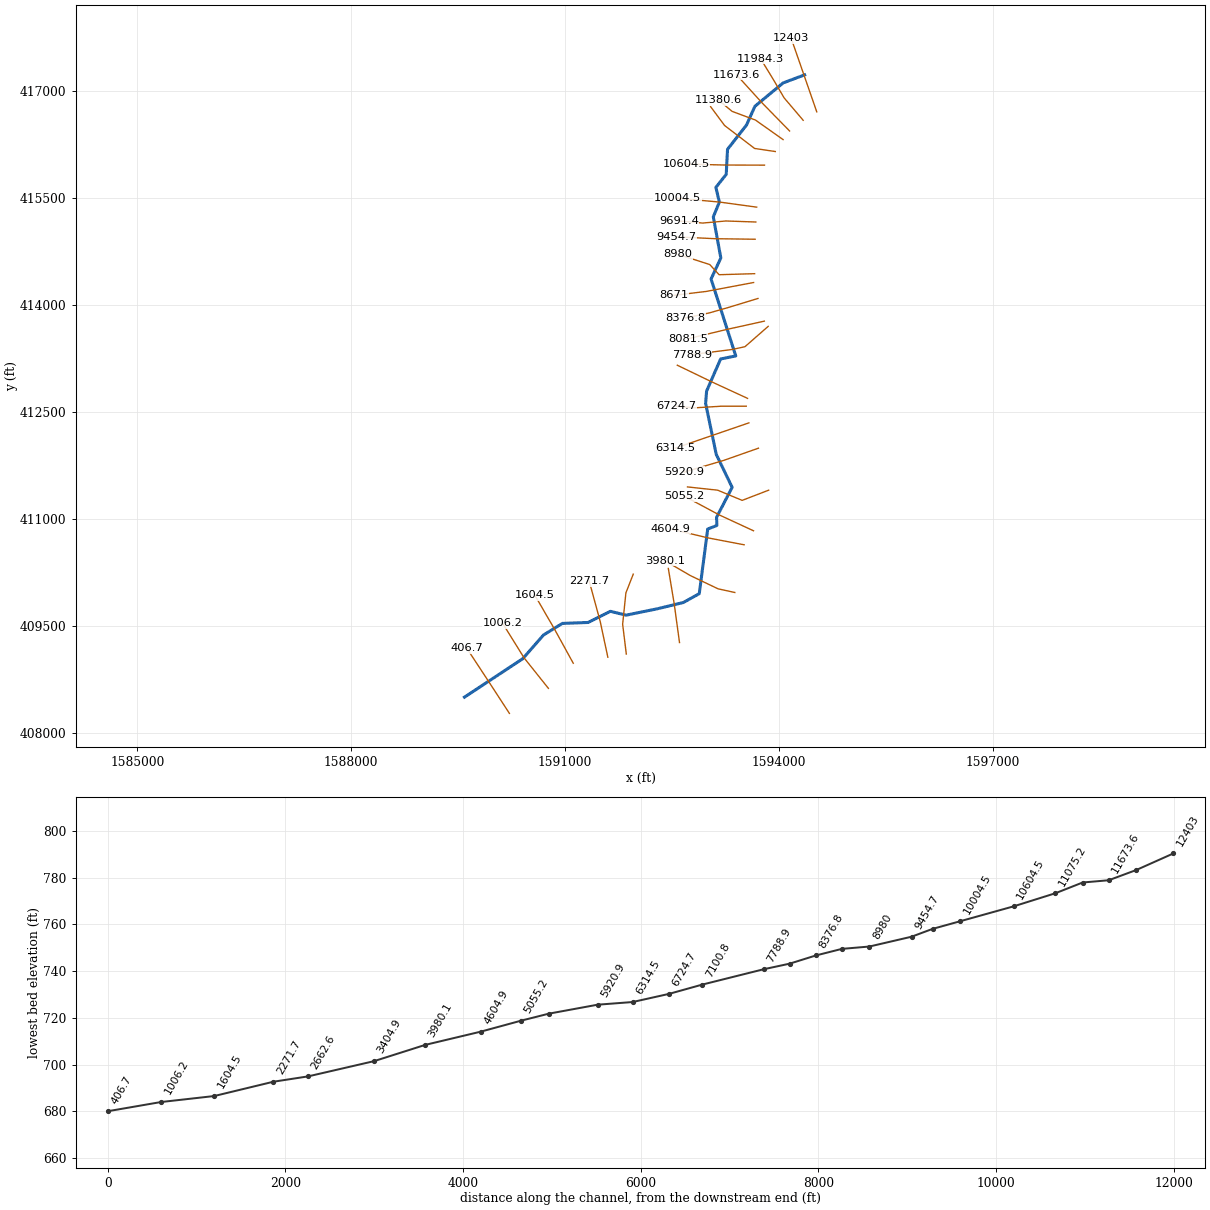
--- LFLICKCR.prj (project) ---

Proj Title=LFLICKCR
Current Plan=p01
Default Exp/Contr=0,0
English Units
Geom File=g01
Flow File=f01
Plan File=p01
BEGIN DESCRIPTION:
END DESCRIPTION:
DSS Export Rating Curves= 0
DSS Export Rating Curve Sorted= 0
DSS Export Volume Flow Curves= 0
DXF OffsetX= 0
DXF OffsetY= 0
DXF ScaleX= 0
DXF ScaleY= 0

--- LFLICKCR.p01 (plan) ---

Plan Title=Floodplain
Program Version=4.00
Geom File=g01
Flow File=f01
K Sum by GR=0
Std Step Tol=0.01
Critical Tol=0.01
Num of Std Step Trials=20
Max Error Tol=0.3
Flow Tol Ratio=0.001
Split Flow NTrial=30
Split Flow Tol=0.02
Split Flow Ratio=0.02
Log Output Level=0
Friction Slope Method=1
Unsteady Friction Slope Method=2
Unsteady Bridges Friction Slope Method=1
Global Log Level=0
CheckData=False
Run HTab=0
Run UNet=0
Run PostProcess=0
UNET Theta=0
UNET Theta Warmup=0
UNET ZTol=0
UNET ZSATol=0
UNET MxIter=0
UNET MaxInSteps=0
UNET DtIC=0
UNET DtMin=0
UNET MaxCRTS=0
UNET WFStab=0
UNET SFStab=0
UNET WFX=0
UNET SFX=0
UNET DSS MLevel=0
UNET DZMax Abort=0
UNET Convert EG Bridges=0
UNET Use Existing IB Tables=0
UNET Froude Limit=0
UNET Froude Power=0
Write IC File=0
Echo Input=False
Echo Output=False
Write Detailed=0

--- LFLICKCR.f01 (steady flow) ---

Flow Title=NFF Regression Equation
Program Version=4.00
Number of Profiles=1
Profile Names=P100yr
River Rch & RM=LFLICKCR,Main      ,12403
     355
River Rch & RM=LFLICKCR,Main      ,11673.6
     368
River Rch & RM=LFLICKCR,Main      ,11380.6
     405
River Rch & RM=LFLICKCR,Main      ,11075.2
     410
River Rch & RM=LFLICKCR,Main      ,8980
     450
River Rch & RM=LFLICKCR,Main      ,8671
     505
River Rch & RM=LFLICKCR,Main      ,8081.5
     515
River Rch & RM=LFLICKCR,Main      ,7788.9
     689
River Rch & RM=LFLICKCR,Main      ,5371.4
     734
River Rch & RM=LFLICKCR,Main      ,2662.6
     808
Boundary for River Rch & Prof#=LFLICKCR,Main      ,1
Up Type=0
Dn Type=3
Dn Slope=0.006678

--- LFLICKCR.g01 (geometry) ---

Geom Title=USGS 10m DEM
Program Version=4.00

River Reach=LFLICKCR        ,Main
Reach XY= 30
     1594361.198      417232.231     1594058.539      417118.568
     1593663.952      416791.207     1593545.288      416527.369
     1593279.246      416186.851      1593260.94      415835.277
     1593115.928      415652.825     1593164.696      415445.117
      1593079.77      415239.048      1593185.25      414661.737
     1593048.436      414366.716     1593394.619       413286.81
     1593182.164       413243.83     1592985.815      412793.481
     1592971.897      412620.234     1593121.386       411903.72
     1593344.018      411442.161       1593125.7      411021.546
     1593129.336      410906.477     1593001.213      410856.572
      1592882.86      409949.509     1592659.105      409825.373
     1592299.233      409738.385     1591856.348       409647.63
     1591636.165      409701.718     1591324.259      409545.201
     1590962.527      409531.823     1590697.994      409369.636
     1590406.438       409036.14      1589588.99      408496.668

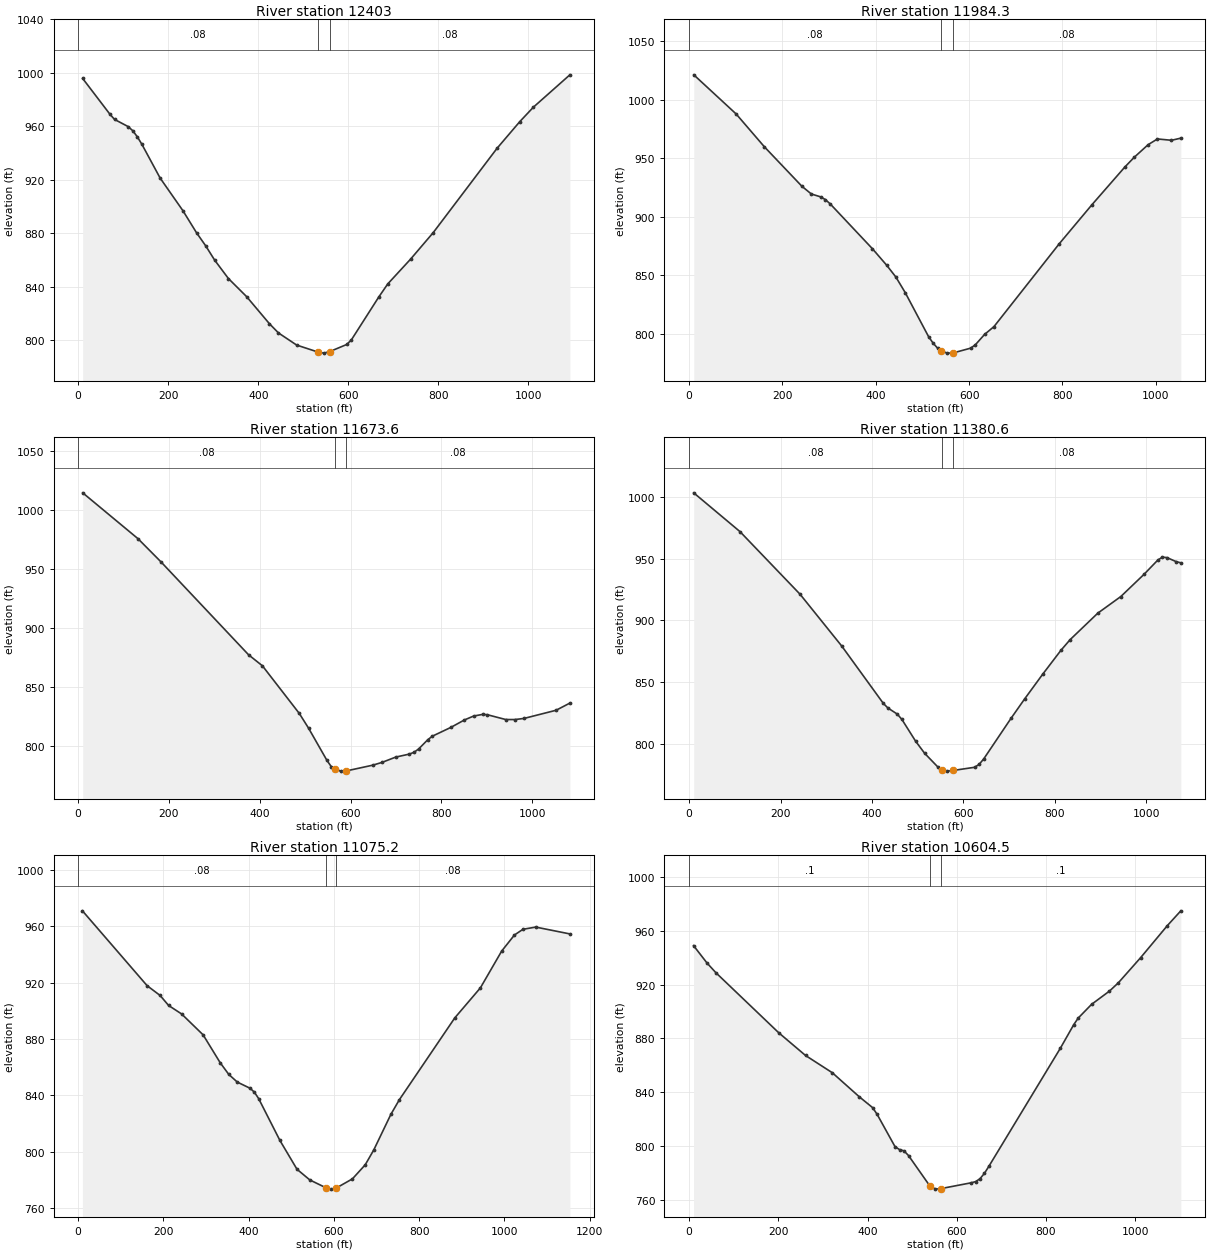
Type RM Length L Ch R = 1 ,12403   ,414.7,418.7,422.7
XS GIS Cut Line= 3
     1594530.878      416713.169     1594351.752       417228.95
     1594172.626      417744.731
#Sta/Elev= 30
    10.1  995.71    70.8   968.9    80.9  965.11   111.2  959.72   121.3  956.67
   131.4  952.12   141.6   946.5     182  921.33   232.6  896.93   262.9  880.41
   283.1   870.7   303.3  859.88   333.7  846.19   374.1  832.66   424.7  812.43
   444.9   805.5   485.3  796.43   533.5  791.12     546  790.41   558.5  791.54
   596.6  796.89   606.7  800.27   667.3  832.19   687.6  842.15   738.1   860.6
   788.7  880.56   930.2  943.49   980.8  963.46  1011.1  974.29    1092  998.44
#Mann= 3 , 0 , 0
       0     .08       0   533.5    .045       0   558.5     .08       0
Bank Sta=533.5,558.5
XS Rating Curve= 0 ,0
Exp/Cntr=0.3,0.1

Type RM Length L Ch R = 1 ,11984.3 ,303.7,310.7,317.8
XS GIS Cut Line= 4
     1594340.292      416594.509     1594072.967       416909.44
     1593915.502      417176.765     1593743.389      417458.738
#Sta/Elev= 30
    10.1 1021.31   100.8  987.85   161.2  959.82   241.8  925.98     262   919.4
   282.1  916.91   292.2  914.54   302.3  910.97   392.9  872.55   423.1  858.62
   443.1  848.38   463.1  835.09   513.2  797.38   523.2  791.68   533.2  787.27
   540.7  785.17   553.2   783.3   565.7  783.45   603.2  787.54   613.3  790.38
   633.3  799.35   653.3  805.97   793.4  876.95   863.5  910.34   933.6  942.39
   953.6  950.69   983.6  961.57  1003.6  966.46  1033.7  965.33  1053.7  967.15
#Mann= 3 , 0 , 0
       0     .08       0   540.7    .045       0   565.7     .08       0
Bank Sta=540.7,565.7
XS Rating Curve= 0 ,0
Exp/Cntr=0.3,0.1

Type RM Length L Ch R = 1 ,11673.6 ,279.5,292.9,306.3
XS GIS Cut Line= 3
     1594149.869      416444.368     1593766.582      416835.941
     1593406.486      417231.695
#Sta/Elev= 30
    10.1  1014.4   131.9  975.57   182.6  955.93   375.4  877.35   405.9  868.02
   487.1  827.72   507.4  815.34   547.9  788.05     558  782.43   565.7  780.43
   578.2  778.92   590.7   779.1   648.9  783.96   669.1  786.28   699.4  790.79
   729.7  793.35   739.8  794.87   749.9  797.67     770  805.48   780.1  808.49
   820.5  815.85   850.8  822.23     871  825.52   891.2  826.95   901.3  826.64
   941.7  822.58   961.9  822.56     982  823.51  1052.7  830.43    1083  836.49
#Mann= 3 , 0 , 0
       0     .08       0   565.7    .045       0   590.7     .08       0
Bank Sta=565.7,590.7
XS Rating Curve= 0 ,0
Exp/Cntr=0.3,0.1

Type RM Length L Ch R = 1 ,11380.6 ,313.5,305.4,297.4
XS GIS Cut Line= 4
     1594058.319      416323.522     1593670.149      416598.171
     1593344.232      416719.017     1593150.147      416880.144
#Sta/Elev= 30
    10.1 1003.27   111.3  971.88   242.8  921.12   333.9   879.2   424.9  832.74
     435  829.03   455.3  824.13   465.4  819.81   495.4  802.21   515.2  792.37
     545  780.94   552.4  779.22   564.9  777.96   577.4   778.5   624.5  781.07
   634.4  783.47   644.3  787.82   703.9  820.62   733.7  836.35   773.5  856.51
   813.2  875.77   833.2  884.37   893.7  905.81   944.2  919.32   994.6  937.17
  1024.9  948.77    1035  951.19  1045.1  950.83  1065.3  947.55  1075.4   946.6
#Mann= 3 , 0 , 0
       0     .08       0   552.4    .045       0   577.4     .08       0
Bank Sta=552.4,577.4
XS Rating Curve= 0 ,0
Exp/Cntr=0.3,0.1

Type RM Length L Ch R = 1 ,11075.2 ,452.9,470.7,488
XS GIS Cut Line= 4
     1593949.209      416155.822     1593659.163      416199.015
     1593238.034      416521.269     1593041.583      416786.261
#Sta/Elev= 30
    10.1  970.88   161.8  917.76   192.1  910.86   212.3   903.7   242.7   897.7
   293.2  882.85   333.3  863.04   353.3  854.81   373.3  849.35   403.3  844.96
   413.3  842.22   423.3  837.69   473.3  807.92   513.4  787.46   543.4  779.91
   580.9  774.39   593.4  773.38   605.9  774.24   643.4  780.67   673.4  790.65
   693.5  801.22   733.5  826.41   753.5  836.86   883.5  894.92   943.5   916.2
   993.5  942.34  1023.4  953.73  1043.4  957.78  1073.4  959.34  1153.4  954.49
#Mann= 3 , 0 , 0
       0     .08       0   580.9    .045       0   605.9     .08       0
Bank Sta=580.9,605.9
XS Rating Curve= 0 ,0
Exp/Cntr=0.3,0.1

Type RM Length L Ch R = 1 ,10604.5 ,605.4,600,595.2
XS GIS Cut Line= 3
     1593798.318      415964.647     1593246.242      415966.288
     1592696.061      415979.295
#Sta/Elev= 30
      10  948.97    40.2  936.02    60.2  928.77   200.8  884.17     261  867.23
   321.2  854.35   381.4  836.52   411.5  828.39   421.6  823.39   461.7  799.35
   471.8  797.17   481.8  796.23   491.9  792.76   539.6   770.2   552.1  767.76
   564.6  768.15   632.1  772.45   642.1  773.32   652.1  775.47   662.1  779.51
   672.2  784.81   832.2  872.53   862.3  890.12   872.3  895.03   902.3  905.25
   942.3   915.1   962.3  921.27  1012.4  940.05  1072.4  963.93  1102.4  974.85
#Mann= 3 , 0 , 0
       0      .1       0   539.6    .045       0   564.6      .1       0
Bank Sta=539.6,564.6
XS Rating Curve= 0 ,0
Exp/Cntr=0.3,0.1

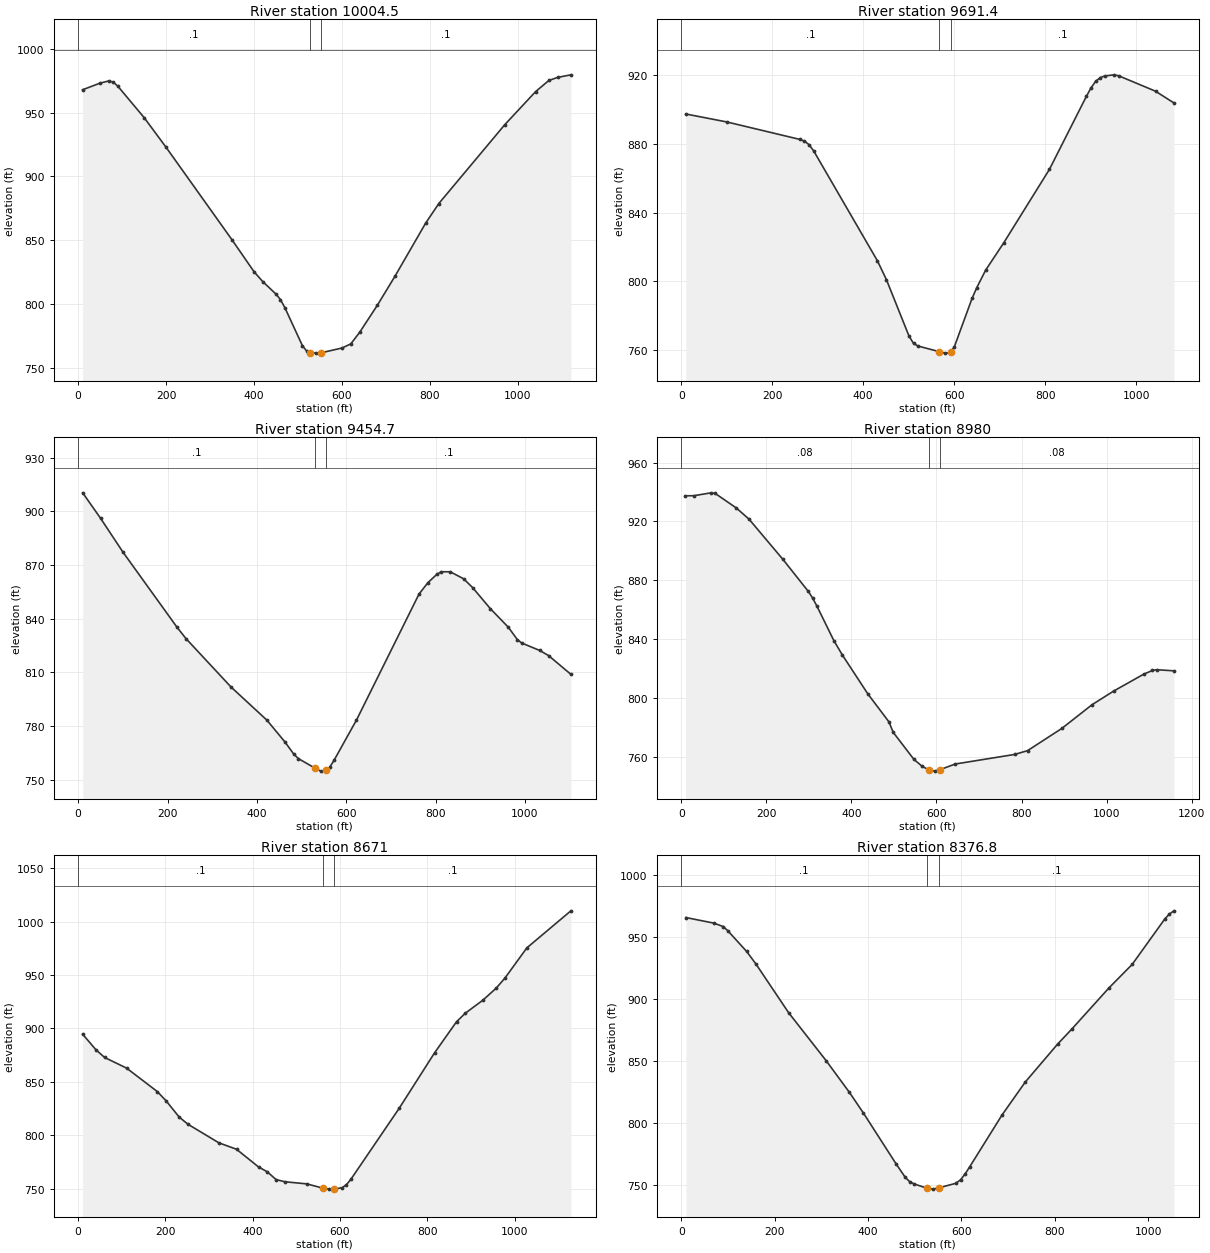
Type RM Length L Ch R = 1 ,10004.5 ,305.8,313.1,320.1
XS GIS Cut Line= 3
     1593688.459      415375.068     1593163.457      415447.027
     1592575.215      415499.575
#Sta/Elev= 30
      10  967.92      50  973.16      70  974.87      80  973.86      90   970.8
     150  946.09     200  922.77   349.9  850.23   399.9  825.26   419.9  817.45
   449.9  807.69   459.9  803.45   469.9  797.17   509.9  767.28   519.9  762.92
   527.4   761.9   539.9  761.41   552.4  761.66     600  765.42     620  768.68
     640  777.65   680.1   798.8   720.1   821.5   790.2  863.34   820.2  878.73
   970.3  940.61  1040.4  966.52  1070.4  975.21  1090.5  977.64  1120.5  979.64
#Mann= 3 , 0 , 0
       0      .1       0   527.4    .045       0   552.4      .1       0
Bank Sta=527.4,552.4
XS Rating Curve= 0 ,0
Exp/Cntr=0.3,0.1

Type RM Length L Ch R = 1 ,9691.4  ,239.5,236.6,232.9
XS GIS Cut Line= 4
     1593677.473      415166.334     1593256.344      415180.982
     1592930.428      415151.686     1592597.187      415180.982
#Sta/Elev= 30
      10  897.49   100.3  892.84   260.9  882.66   270.9  881.69   280.9  879.61
     291  876.06   431.3  811.92   451.1  800.93   500.7  768.06   510.6  763.81
   520.5  762.24   567.5  758.95     580  758.11     590  758.23   592.5  759.04
   599.9  761.46   639.5  790.13   649.5  796.18   669.3  806.53   708.9  822.36
   809.4  865.21   890.5  907.69   900.7  912.67   910.8  916.46   920.9  918.62
   931.1  919.65   951.4  920.31   961.5  919.76  1042.6  910.77  1083.1  903.92
#Mann= 3 , 0 , 0
       0      .1       0   567.5    .045       0   592.5      .1       0
Bank Sta=567.5,592.5
XS Rating Curve= 0 ,0
Exp/Cntr=0.3,0.1

Type RM Length L Ch R = 1 ,9454.7  ,497.2,474.7,453.1
XS GIS Cut Line= 3
     1593666.487      414924.643     1593113.527      414931.967
     1592564.229      414957.601
#Sta/Elev= 30
    10.1  910.38    50.3  896.08   100.5  877.13   221.2  835.23   241.3  828.87
   341.9  801.86   422.3   783.3   462.5  771.18   482.6  764.28   492.7  761.81
   530.5  756.36     543  754.76   555.5  755.31     563  756.91     573  760.93
     623  783.34     763   853.8     783  860.18     803  864.84     813  866.26
     833  866.22   862.9   862.3   882.9  857.39   922.9  845.53   962.9  835.21
   982.9  828.36   992.9  826.38  1032.9  822.26  1052.9  819.38  1102.9  808.89
#Mann= 3 , 0 , 0
       0      .1       0   530.5    .045       0   555.5      .1       0
Bank Sta=530.5,555.5
XS Rating Curve= 0 ,0
Exp/Cntr=0.3,0.1

Type RM Length L Ch R = 1 ,8980    ,280,309,338.1
XS GIS Cut Line= 4
     1593659.163      414441.261     1593161.133      414426.613
     1593029.301      414569.431     1592586.201      414712.248
#Sta/Elev= 30
      10  937.41    29.9  937.46    69.8  939.42    79.7  939.04   129.5  929.14
   159.4  921.55   239.2  894.21   298.9  872.47   308.9  868.01   318.9  862.59
   358.7  839.19   378.7  829.41   438.5  803.05   488.3  783.98   498.2  776.94
   546.8  758.59   566.3  753.85   582.9  751.25   595.4  750.56   607.9  751.49
     644  755.38   783.7  761.88   814.1  764.45     895   779.6   965.9  795.67
  1016.5  804.89  1087.3  816.38  1107.6  818.87  1117.7  819.37  1158.2  818.63
#Mann= 3 , 0 , 0
       0     .08       0   582.9    .045       0   607.9     .08       0
Bank Sta=582.9,607.9
XS Rating Curve= 0 ,0
Exp/Cntr=0.3,0.1

Type RM Length L Ch R = 1 ,8671    ,291.7,294.2,296.7
XS GIS Cut Line= 3
     1593645.326      414317.147     1592981.695      414192.246
     1592531.271      414137.316
#Sta/Elev= 30
    10.1   894.7    40.3  880.23    60.5  872.85   110.9  862.88   181.4  840.88
   201.6  832.19   231.8  816.85     252   810.2   322.5  792.89   362.8  786.89
   413.2  770.36   433.4  765.74   453.5  758.48   473.7  756.46   524.1  754.46
     562  750.34   574.5  749.56     587  749.76   604.7  750.86   614.8  753.76
   624.9  758.76   735.8   825.4   816.5   877.1   866.9  906.26     887  914.25
   927.4   926.5   957.6  937.63   977.8  947.14  1028.2   975.5    1129 1010.14
#Mann= 3 , 0 , 0
       0      .1       0     562    .045       0     587      .1       0
Bank Sta=562,587
XS Rating Curve= 0 ,0
Exp/Cntr=0.3,0.1

Type RM Length L Ch R = 1 ,8376.8  ,296.9,295.3,293.7
XS GIS Cut Line= 4
     1593706.769      414093.373      1593285.64      413965.203
     1593029.301      413891.963     1592688.737      413818.723
#Sta/Elev= 30
      10  965.45      70  960.95      90  958.18     100  954.74   140.1  938.14
   160.1  927.98   230.1  888.76   310.1  850.31   360.2  824.64   390.2  807.98
   459.9   767.2   479.7  756.25   489.6  752.57   499.4  750.82   526.4  747.45
   538.9  746.73   551.4  747.74   588.3  751.45   598.2  754.28   608.1  759.04
   617.9  764.77     687  806.45   736.7  832.97   806.3  863.65   836.2  875.54
   915.8  908.72   965.6  927.67  1035.2  964.13  1045.2  968.24  1055.1  970.86
#Mann= 3 , 0 , 0
       0      .1       0   526.4    .045       0   551.4      .1       0
Bank Sta=526.4,551.4
XS Rating Curve= 0 ,0
Exp/Cntr=0.3,0.1

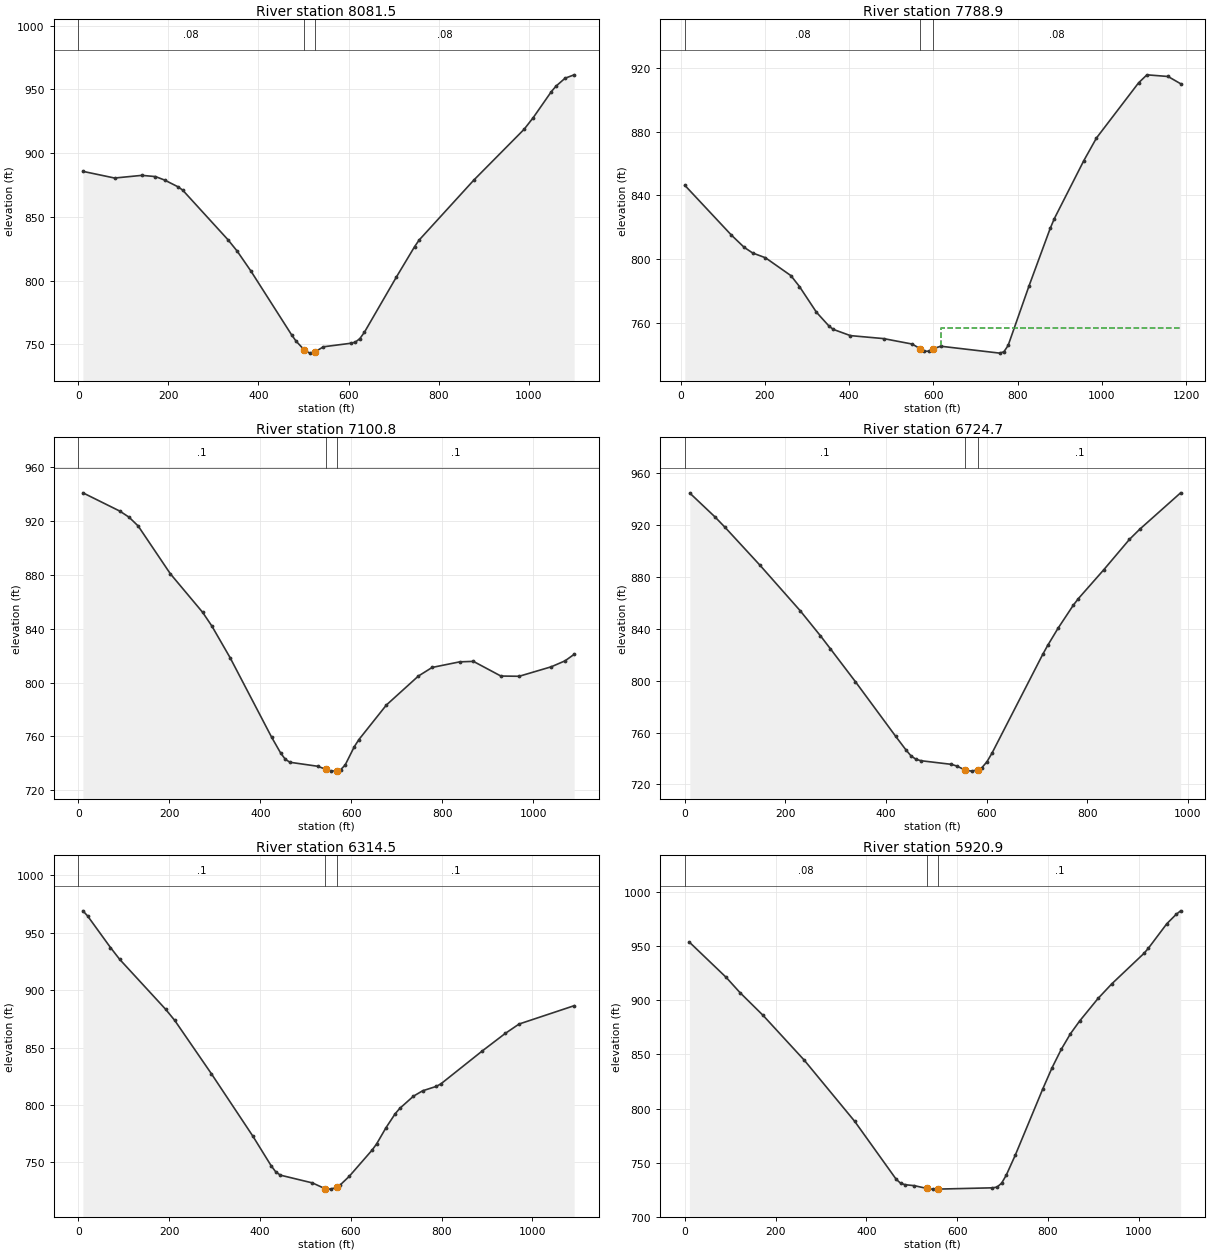
Type RM Length L Ch R = 1 ,8081.5  ,292.7,292.6,292.5
XS GIS Cut Line= 3
     1593795.662      413774.836     1593264.375      413657.514
     1592722.995      413527.122
#Sta/Elev= 30
    10.1  885.79    80.6  880.55   141.1  882.65   171.3  881.68   191.4     879
   221.7   873.6   231.7  871.07   332.5  832.06   352.6  823.27   382.9  807.74
   473.6  757.52   483.6  752.56   501.4  745.85   513.9  743.22   526.4  744.38
   544.1  748.18   604.8  750.95     615  751.84   625.1  754.61   635.2   759.6
   706.1  802.84   746.6  826.72   756.7  831.91   878.2  878.97   989.6  918.72
  1009.8  927.82  1050.3  948.35  1060.4  952.55  1080.7  958.84  1100.9   961.5
#Mann= 3 , 0 , 0
       0     .08       0   501.4    .045       0   526.4     .08       0
Bank Sta=501.4,526.4
XS Rating Curve= 0 ,0
Exp/Cntr=0.3,0.1

Type RM Length L Ch R = 1 ,7788.9  ,706.1,688.1,669.5
XS GIS Cut Line= 4
     1593849.586       413701.54     1593523.669      413415.905
     1593343.615      413376.939     1592778.897      413305.269
#Sta/Elev= 30
    10.1  846.26   120.9  814.91   151.2  807.24   171.3  803.72   201.6  800.72
     262   789.5   282.2  782.67   322.5  766.53   352.7  757.72   362.8  755.71
   403.1  751.83   481.8  749.96   549.7  746.53   569.1  743.53   578.8  741.99
   588.5  742.04   598.2  743.51   617.6  745.16   757.4  740.83   767.4  741.67
   777.4  745.63   827.3  783.26   877.2  819.12   887.2  825.39   957.1  861.77
   987.1  875.97    1087   910.6  1106.9  915.64  1156.9   914.6  1186.8  910.05
#Mann= 3 , 0 , 0
    10.1     .08       0   569.1    .045       0   598.2     .08       0
#XS Ineff= 2 , 0
                          619.24          756.74
Permanent Ineff=
       F       F
Bank Sta=569.1,598.2
XS Rating Curve= 0 ,0
Exp/Cntr=0.3,0.1

Type RM Length L Ch R = 1 ,7100.8  ,362.6,376.1,390.2
XS GIS Cut Line= 3
     1593560.289      412690.832     1593055.407      412923.819
     1592575.215      413155.904
#Sta/Elev= 30
    10.1  940.69      91  927.16   111.2  922.68   131.4  916.13   202.2  880.64
     273  852.11   293.2  841.99   333.6  818.34   424.6  759.51   444.8  747.55
   454.9  743.04   465.1  740.85   525.7  737.91   543.5  735.69     556  734.29
   568.5  734.55   576.2  735.29   586.2   738.8   606.4  752.45   616.4  757.68
   676.8  783.31   747.2  804.82   777.4  811.19   837.8  815.33     868  815.69
   928.4  804.81   968.6  804.64  1039.1  811.68  1069.3  816.07  1089.4  820.91
#Mann= 3 , 0 , 0
       0      .1       0   543.5    .045       0   568.5      .1       0
Bank Sta=543.5,568.5
XS Rating Curve= 0 ,0
Exp/Cntr=0.3,0.1

Type RM Length L Ch R = 1 ,6724.7  ,402.7,410.2,417.6
XS GIS Cut Line= 4
     1593541.636      412580.858     1593192.603      412580.858
     1592820.682       412557.97     1592557.477      412580.858
#Sta/Elev= 30
      10  944.61    59.8  926.34    79.8  918.32   149.6  888.96   229.4  853.96
   269.3  834.83   289.2  824.77   339.1  799.33   419.5  757.03   439.7  746.68
   449.7   742.1   459.8  739.39   469.9  738.31   530.3  735.52   540.4  734.28
   558.1  731.05   570.6   730.3   583.1  731.38   590.7  732.94   600.8  737.52
   610.9  744.22   711.6  820.21   721.7  827.29     742  840.33   772.5   858.2
   782.6  863.29   833.4  885.66   884.2  908.96   904.6  916.75   985.9  944.82
#Mann= 3 , 0 , 0
       0      .1       0   558.1    .045       0   583.1      .1       0
Bank Sta=558.1,583.1
XS Rating Curve= 0 ,0
Exp/Cntr=0.3,0.1

Type RM Length L Ch R = 1 ,6314.5  ,395.7,393.6,390.2
XS GIS Cut Line= 3
     1593578.782      412346.789     1593062.385      412169.447
     1592545.989      411992.104
#Sta/Elev= 30
    10.1  969.16    20.2  964.81    70.8   937.2      91  926.94   192.1   883.5
   212.3  873.74   293.2  827.21   384.2  773.05   424.7  747.15   434.8  741.85
   444.9  738.99   515.7   732.2   543.6  727.16   556.1  726.81   568.6  728.51
   576.3  730.28   596.6  737.93   647.1  760.85   657.2  766.37   677.4  780.17
   697.7  792.38   707.8  797.08   738.1  807.76   758.3  812.44   788.7  816.32
   798.8  818.57   889.8  847.19   940.3  862.41   970.7  870.58    1092  886.54
#Mann= 3 , 0 , 0
       0      .1       0   543.6    .045       0   568.6      .1       0
Bank Sta=543.6,568.6
XS Rating Curve= 0 ,0
Exp/Cntr=0.3,0.1

Type RM Length L Ch R = 1 ,5920.9  ,567.4,549.6,533.1
XS GIS Cut Line= 3
     1593713.292      411991.507     1593226.414      411820.423
     1592673.777      411656.558
#Sta/Elev= 30
    10.1  953.73    91.1  921.24   121.4  907.22     172  886.31   263.1   844.8
   374.4  788.25   465.5  734.93   475.6  731.06   485.7  729.75   505.9  728.86
   533.9  726.25   546.4  725.67   558.9   725.7   677.9  726.88     688  727.54
   698.1   731.2   708.2  738.49   728.4  757.27   789.1  818.52   809.3  837.82
   829.6  854.83   849.8  869.19     870   880.9   910.5   901.7   940.8  915.21
  1011.6   943.3  1021.7  948.23  1062.1  970.74  1082.4  979.25  1092.5  982.64
#Mann= 3 , 0 , 0
       0     .08       0   533.9    .045       0   558.9      .1       0
Bank Sta=533.9,558.9
XS Rating Curve= 0 ,0
Exp/Cntr=0.3,0.1

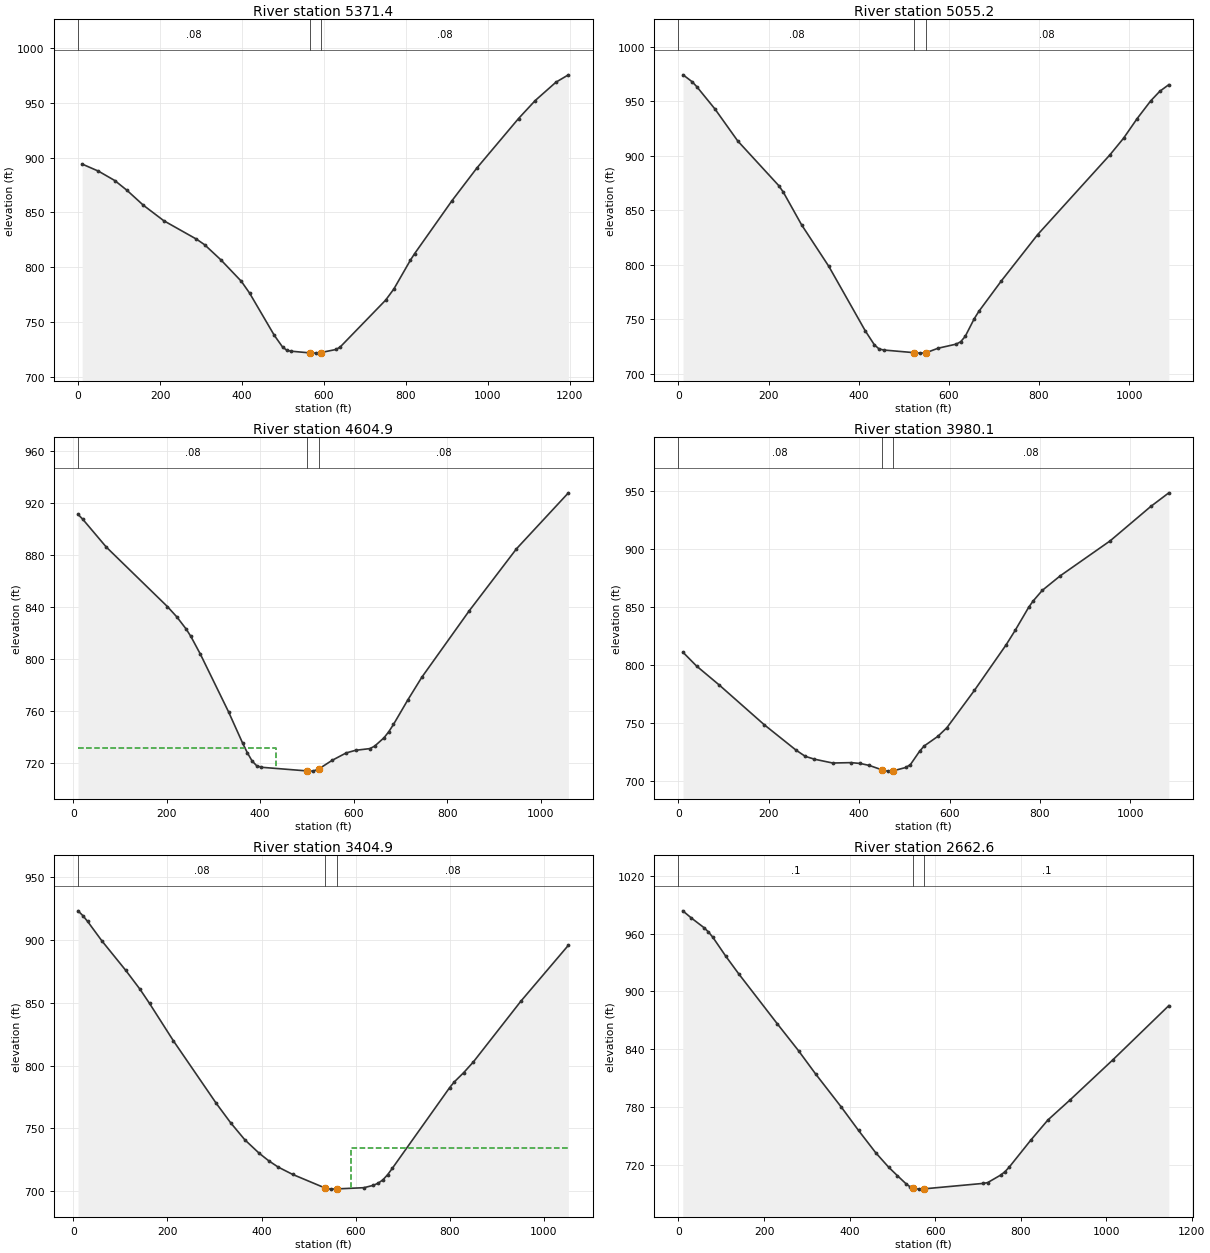
Type RM Length L Ch R = 1 ,5371.4  ,318.3,316.1,313.5
XS GIS Cut Line= 4
     1593856.338      411402.156     1593484.417       411259.11
     1593141.106      411402.156     1592717.689      411447.931
#Sta/Elev= 30
      10  894.11    49.8  887.65    89.7  879.08   119.5  870.14   159.4  856.57
   209.2  842.47   288.9   825.7   308.8   820.6   348.7  806.74   398.5  787.21
   418.6  776.45   478.9  737.97     499  727.37   509.1  724.49   519.1  723.61
   566.9     722   579.4  721.83   591.9  722.31   629.7  725.19   639.7  727.49
   750.3  770.08   770.4  780.25     811  806.65   821.1   812.5   912.4  860.81
   973.2  890.62  1074.6   935.6  1115.2  951.96  1165.9  968.72  1196.3  975.43
#Mann= 3 , 0 , 0
       0     .08       0   566.9    .045       0   591.9     .08       0
Bank Sta=566.9,591.9
XS Rating Curve= 0 ,0
Exp/Cntr=0.3,0.1

Type RM Length L Ch R = 1 ,5055.2  ,442.8,450.3,457
XS GIS Cut Line= 3
     1593643.444      410832.443     1593166.328       411053.32
     1592670.729      411318.801
#Sta/Elev= 30
    10.1  974.49    30.3  968.12    40.4   963.7    80.9  943.09   131.4  913.75
   222.4  872.72   232.5  866.75     273  836.75   333.7  798.39   414.5  739.22
   434.8  726.31   444.9  722.71     455  721.66   523.3   719.2   535.8  718.79
   548.3     719     576   723.3   616.1  727.05   626.2  729.28   636.2  734.21
   656.3  750.49   666.3  757.09   716.5  785.23   796.8  827.63   957.5  901.09
   987.6  916.29  1017.7  934.31  1047.8   950.6  1067.9  959.37    1088  965.47
#Mann= 3 , 0 , 0
       0     .08       0   523.3    .045       0   548.3     .08       0
Bank Sta=523.3,548.3
XS Rating Curve= 0 ,0
Exp/Cntr=0.3,0.1

Type RM Length L Ch R = 1 ,4604.9  ,632,624.8,618.8
XS GIS Cut Line= 3
     1593513.027      410635.427     1593008.816      410731.744
     1592477.371       410858.58
#Sta/Elev= 30
    10.1  911.58    20.1  907.86    70.5  886.43   201.3  840.69   221.4  832.79
   241.6  823.35   251.6  817.69   271.8  804.16   332.2  759.74   362.3  735.71
   372.4  728.29   382.5  722.01   392.5  718.24   402.6   717.1   500.8  714.27
   513.3  714.13   525.8  715.89   553.8   722.4   584.2  728.16   604.4  730.16
   634.7  731.45   644.9  733.32   665.1  739.82   675.2  744.43   685.3  750.06
   715.7  768.74     746  786.37   847.2  837.32   948.4  885.04  1059.7  928.14
#Mann= 3 , 0 , 0
    10.1     .08       0   500.8    .045       0   525.8     .08       0
#XS Ineff= 2 , 0
          433.39  731.75
Permanent Ineff=
       F       F
Bank Sta=500.8,525.8
XS Rating Curve= 0 ,0
Exp/Cntr=0.3,0.1

Type RM Length L Ch R = 1 ,3980.1  ,602.2,575.2,549
XS GIS Cut Line= 4
     1593381.424      409965.971     1593146.828      410017.467
     1592763.464      410200.567     1592399.721      410411.292
#Sta/Elev= 30
      10  810.77      40  798.94    90.1  782.64   190.1  748.31   260.4  726.48
   280.6   721.2   300.9  718.75   341.3  715.45   381.8  715.78     402  715.09
   422.3  713.38   450.2  709.59   462.7  708.47   475.2  708.72   503.2  711.62
   513.3  714.07   533.5  725.48   543.6  730.06     574  738.38   594.2  745.89
   654.9  777.92   725.1  817.14   745.1  829.56   775.1  849.48   785.1  854.99
   805.2  864.06   845.2  876.66   955.3  906.65  1045.4  936.32  1085.4  948.05
#Mann= 3 , 0 , 0
       0     .08       0   450.2    .045       0   475.2     .08       0
Bank Sta=450.2,475.2
XS Rating Curve= 0 ,0
Exp/Cntr=0.3,0.1

Type RM Length L Ch R = 1 ,3404.9  ,748,742.3,735.3
XS GIS Cut Line= 3
     1592605.613      409263.524     1592531.613      409805.287
     1592448.762       410303.56
#Sta/Elev= 30
    10.1  923.25    20.3  919.42    30.4   914.8    60.8  899.27   111.4  875.82
   141.8  860.72     162  849.45   212.6  819.73   303.8  769.83   334.2  754.43
   364.5  740.79   394.9  730.11   415.2   724.1   435.4  719.07   465.8  713.28
   534.3  702.51   546.8  701.52   559.3  701.69   617.5  702.66   637.7  704.59
   647.8  706.26   657.9  708.97     668   713.1   678.1  718.27   799.4   782.3
   809.5  786.96   829.7  794.44   849.9  802.83   950.9  851.25  1051.9  895.83
#Mann= 3 , 0 , 0
    10.1     .08       0   534.3    .045       0   559.3     .08       0
#XS Ineff= 2 , 0
                          590.35          734.31
Permanent Ineff=
       F       F
Bank Sta=534.3,559.3
XS Rating Curve= 0 ,0
Exp/Cntr=0.3,0.1

Type RM Length L Ch R = 1 ,2662.6  ,381.6,391,400.7
XS GIS Cut Line= 4
     1591859.411      409101.971     1591807.914      409519.666
     1591853.689      409960.249     1591956.683      410223.454
#Sta/Elev= 30
      10  983.56    30.1  976.12    60.1  965.95    70.1  961.58    80.2  956.22
   110.2  936.73   140.3  918.53   230.5  866.73   280.6  838.54   320.7  814.36
   380.8  780.01   420.9  755.88   461.1  732.76   491.3  717.78   511.5   709.1
   531.6  700.73   541.7  697.31   549.3  695.91   561.8     695   574.3  695.29
   712.8  700.96   722.9  701.78   753.1  709.53   763.1  712.99   773.2  717.78
   823.5  745.68   863.8  766.74   914.3     787  1015.2   828.9  1146.5   885.3
#Mann= 3 , 0 , 0
       0      .1       0   549.3    .045       0   574.3      .1       0
Bank Sta=549.3,574.3
XS Rating Curve= 0 ,0
Exp/Cntr=0.3,0.1

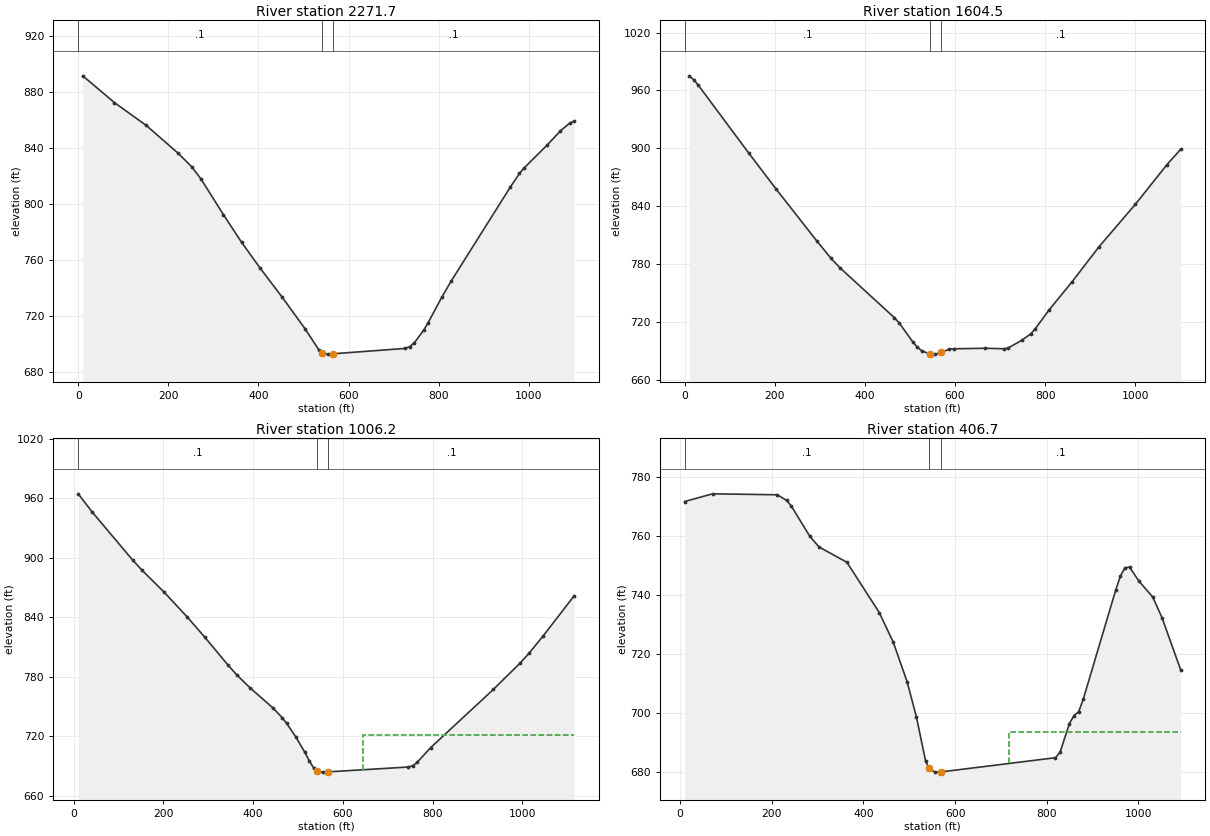
Type RM Length L Ch R = 1 ,2271.7  ,660.5,667.2,674.5
XS GIS Cut Line= 3
     1591600.258      409057.624     1591493.212      409559.719
     1591338.722      410126.183
#Sta/Elev= 30
    10.1  891.25    80.5  872.12     151  855.86   221.5  836.09   251.7  826.45
   271.8  817.95   322.1  792.29   362.4  772.56   402.7   754.5     453  733.16
   503.3  710.86   533.6  695.93   541.4  693.86   543.7  693.25   553.9  692.71
   566.4  692.97     726   696.8   736.1  698.14   746.2  700.99   766.5  709.69
   776.6  715.22     807  733.46   827.2  744.62   958.8  811.86   979.1  821.59
   989.2  825.43  1039.8  841.62  1070.2  852.02  1090.4  857.43  1100.5   858.9
#Mann= 3 , 0 , 0
       0      .1       0   541.4    .045       0   566.4      .1       0
Bank Sta=541.4,566.4
XS Rating Curve= 0 ,0
Exp/Cntr=0.3,0.1

Type RM Length L Ch R = 1 ,1604.5  ,594.5,598.3,599
XS GIS Cut Line= 3
     1591115.328      408972.539      1590847.22      409460.444
     1590574.415      409931.222
#Sta/Elev= 30
    10.1  975.18    20.2  971.11    30.4  965.38   141.7  895.39   202.4  858.08
   293.5  803.83   323.9  786.41   344.2  776.31   465.6  724.31   475.7   719.2
   506.1  699.44   516.2  693.95   526.4  689.89   544.2  686.96   556.7  686.58
   569.2  688.28   586.9  691.68     597  692.12   667.6  692.66   707.9  692.13
   717.9  692.99   748.2  700.89   768.3  707.67   778.4  713.04   808.6  732.28
     859  761.09   919.5  797.83  1000.1  841.81  1070.6  883.16  1100.8  898.91
#Mann= 3 , 0 , 0
       0      .1       0   544.2    .045       0   569.2      .1       0
Bank Sta=544.2,569.2
XS Rating Curve= 0 ,0
Exp/Cntr=0.3,0.1

Type RM Length L Ch R = 1 ,1006.2  ,601.4,599.5,600.2
XS GIS Cut Line= 3
      1590766.62      408620.417     1590426.576      409046.702
     1590125.689       409531.11
#Sta/Elev= 30
    10.1   964.4    40.4  946.56   131.3  897.75   151.5  887.82     202  865.17
   252.5  840.59   292.8  819.68   343.3   792.2   363.5  782.01   393.8  768.64
   444.3  748.66   464.5  739.03   474.6   733.2   494.8   719.7     515  704.22
   525.1  695.46   535.2  687.97   542.8  685.26   545.3  684.37   555.3  684.02
   567.8  684.31   745.4  689.16   755.4  690.42   765.4  693.76   795.4  708.61
   935.5  767.38   995.5  794.09  1015.5  804.09  1045.5  820.71  1115.5  861.67
#Mann= 3 , 0 , 0
    10.1      .1       0   542.8    .045       0   567.8      .1       0
#XS Ineff= 2 , 0
                           644.9          721.27
Permanent Ineff=
       F       F
Bank Sta=542.8,567.8
XS Rating Curve= 0 ,0
Exp/Cntr=0.3,0.1

Type RM Length L Ch R = 1 ,406.7   ,401.8,406.7,411.6
XS GIS Cut Line= 3
     1590219.491      408269.092      1589921.66      408726.675
     1589621.851      409183.049
#Sta/Elev= 30
    10.1  771.63    70.8  774.23   212.3  773.91   232.5  771.98   242.7  770.11
   283.1  759.85   303.3  756.25     364  751.07   434.8  734.01   465.1  724.02
   495.4  710.63   515.6  698.76   535.9  683.69   543.6  681.31   556.1  680.08
   568.6  680.14     819  684.96   829.1  686.82   849.3  696.48   859.4  699.19
   869.6  700.54   879.7  704.79   950.4  741.66   960.6  746.41   970.7  749.25
   980.8   749.4    1001  744.71  1031.3   739.3  1051.6  732.23    1092  714.74
#Mann= 3 , 0 , 0
    10.1      .1       0   543.6    .045       0   568.6      .1       0
#XS Ineff= 2 , 0
                          718.14          693.79
Permanent Ineff=
       F       F
Bank Sta=543.6,568.6
XS Rating Curve= 0 ,0
Exp/Cntr=0.3,0.1

Chan Stop Cuts=-1
Use User Specified Reach Order=0